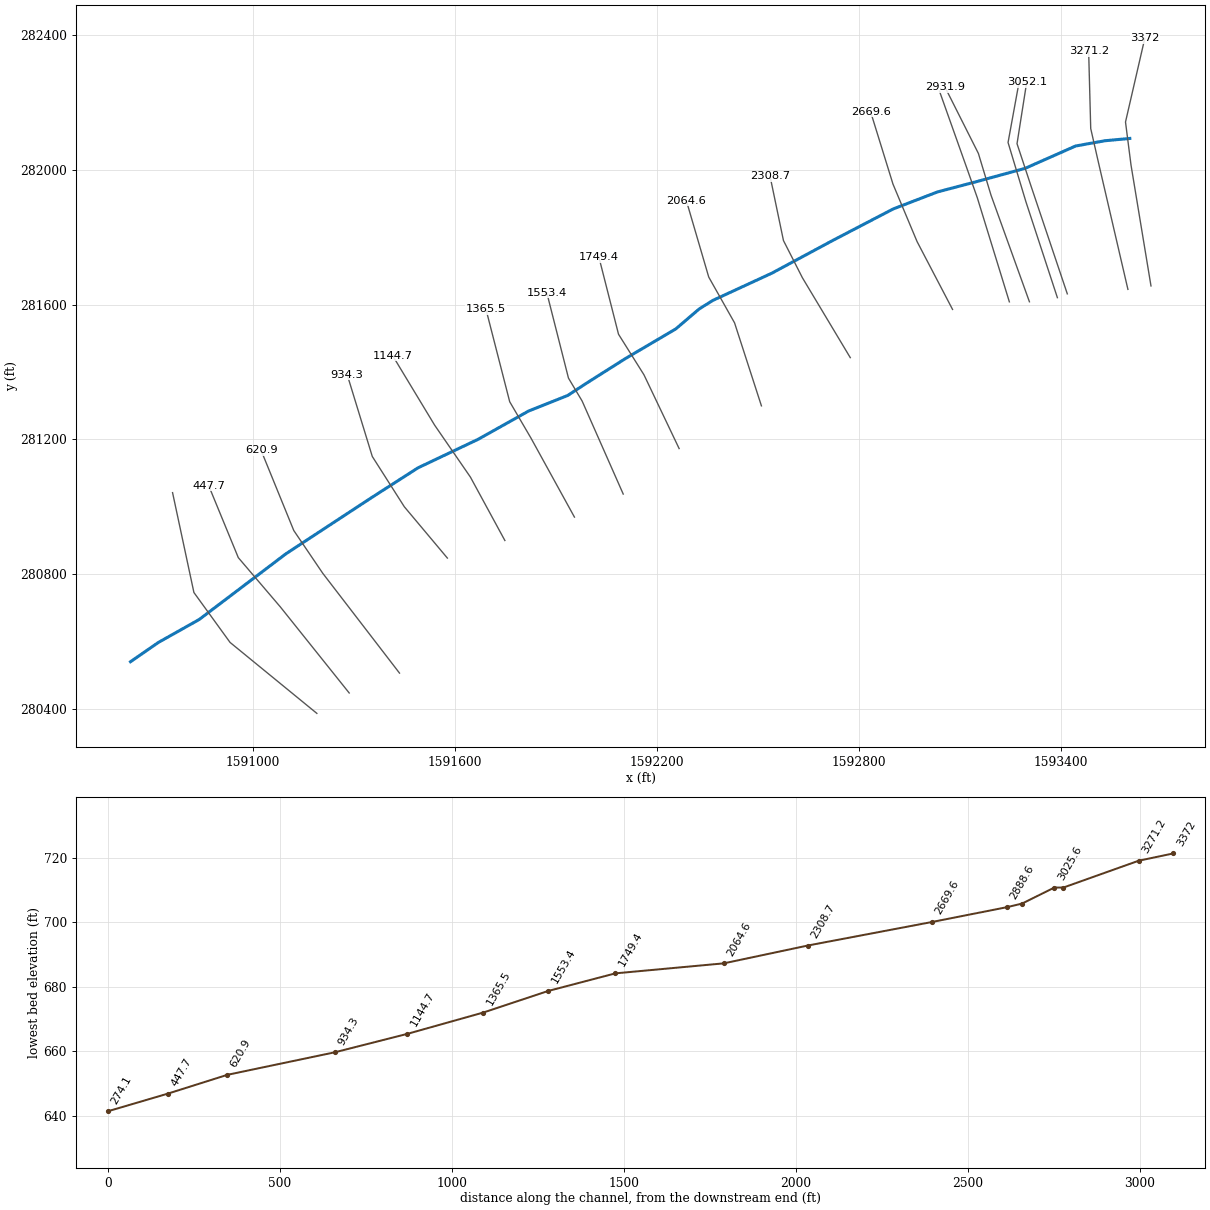
--- rdbrnch.prj (project) ---

Proj Title=rdbrnch
Current Plan=p01
Default Exp/Contr=0,0
English Units
Geom File=g01
Flow File=f01
Plan File=p01
BEGIN DESCRIPTION:
END DESCRIPTION:
DSS Export Rating Curves= 0
DSS Export Rating Curve Sorted= 0
DSS Export Volume Flow Curves= 0
DXF OffsetX= 0
DXF OffsetY= 0
DXF ScaleX= 0
DXF ScaleY= 0

--- rdbrnch.p01 (plan) ---

Plan Title=Floodplain
Program Version=4.00
Geom File=g01
Flow File=f01
K Sum by GR=0
Std Step Tol=0.01
Critical Tol=0.01
Num of Std Step Trials=20
Max Error Tol=0.3
Flow Tol Ratio=0.001
Split Flow NTrial=30
Split Flow Tol=0.02
Split Flow Ratio=0.02
Log Output Level=0
Friction Slope Method=1
Unsteady Friction Slope Method=2
Unsteady Bridges Friction Slope Method=1
Global Log Level=0
CheckData=False
Run HTab=0
Run UNet=0
Run PostProcess=0
UNET Theta=0
UNET Theta Warmup=0
UNET ZTol=0
UNET ZSATol=0
UNET MxIter=0
UNET MaxInSteps=0
UNET DtIC=0
UNET DtMin=0
UNET MaxCRTS=0
UNET WFStab=0
UNET SFStab=0
UNET WFX=0
UNET SFX=0
UNET DSS MLevel=0
UNET DZMax Abort=0
UNET Convert EG Bridges=0
UNET Use Existing IB Tables=0
UNET Froude Limit=0
UNET Froude Power=0
Write IC File=0
Echo Input=False
Echo Output=False
Write Detailed=0

--- rdbrnch.f01 (steady flow) ---

Flow Title=NFF Regression Equation
Program Version=4.00
Number of Profiles= 1
Profile Names=P100yr
River Rch & RM=rdbrnch,Main            ,3372
     344
River Rch & RM=rdbrnch,Main            ,3271.2
     344
River Rch & RM=rdbrnch,Main            ,2931.9
     397
River Rch & RM=rdbrnch,Main            ,2064.6
     417
River Rch & RM=rdbrnch,Main            ,274.1
     455
Boundary for River Rch & Prof#=rdbrnch,Main            , 1
Up Type= 0
Dn Type= 3
Dn Slope=0.02
DSS Import GetInterval= 0
DSS Import GetPeak= 0
DSS Import FillOption= 0

--- rdbrnch.g01 (geometry) ---

Geom Title=USGS 10m DEM
Program Version=4.00

River Reach=rdbrnch         ,Main
Reach XY= 23
     1593604.232      282093.376     1593530.979      282086.622
     1593443.578      282070.997     1593293.577      282004.663
     1593155.525      281966.813     1593033.035      281934.506
     1592901.917      281884.087     1592721.677      281790.159
     1592541.834      281693.541     1592366.913      281612.788
     1592326.433      281587.656     1592255.998      281527.657
     1592107.247      281440.129     1591990.968      281366.552
     1591935.209      281330.157      1591819.51      281284.166
     1591669.351      281200.079     1591491.027      281115.472
     1591354.336      281027.778     1591099.094      280860.377
     1590841.225      280665.056     1590720.024      280596.926
     1590637.281      280539.715

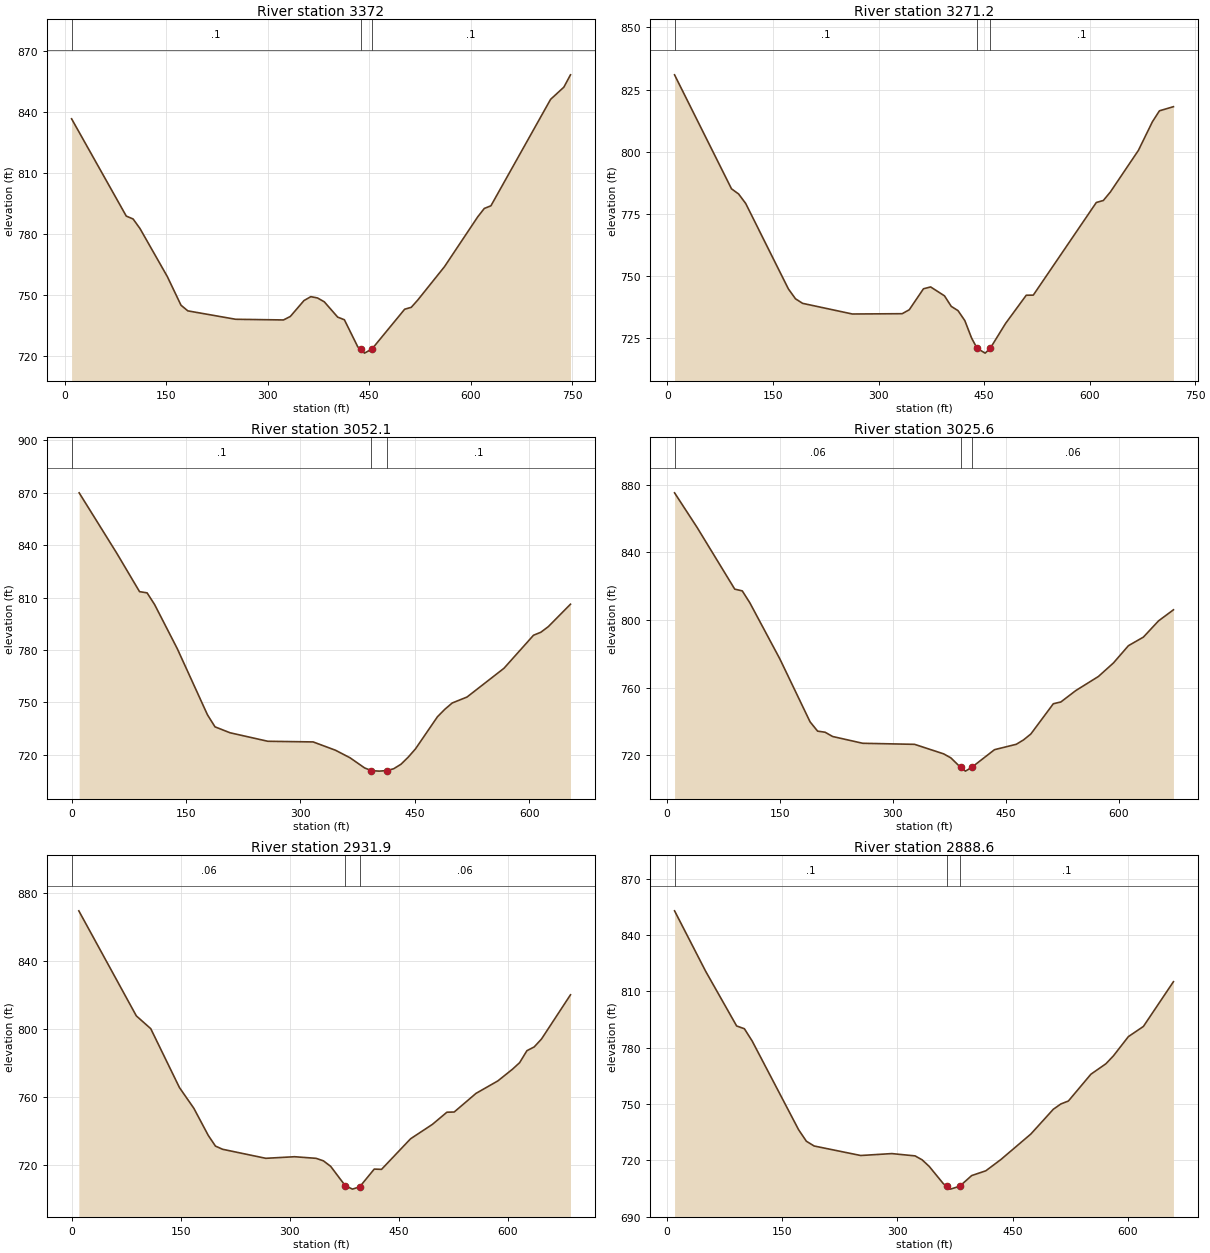
Type RM Length L Ch R = 1 ,3372    ,98.4,100.8,103.2
XS GIS Cut Line= 4
     1593667.183        281655.5     1593607.884      282014.367
     1593591.525      282142.169      1593648.78      282390.615
#Sta/Elev= 30
    10.1  836.46    90.9  788.68     101  787.25   111.1   782.6   151.6  758.95
   171.8  744.89   181.9  742.11   252.6  737.98   323.3  737.65   333.4  739.37
   353.6  747.18   363.7  749.09   373.6  748.45   383.6  746.56   403.4  739.04
   413.3  737.74   433.1  724.44  437.17  723.21     443  721.35  454.09  723.38
   502.4  742.92   512.2  743.86     522  747.53   561.2   763.8   610.3  788.25
   620.1  792.43   629.9  793.74   718.1  846.03   737.7  852.02   747.5  858.08
#Mann= 3 , 0 , 0
    10.1      .1       0  437.17    .045       0  454.09      .1       0
Bank Sta=437.17,454.09
XS Rating Curve= 0 ,0
Exp/Cntr=0.3,0.1

Type RM Length L Ch R = 1 ,3271.2  ,216.7,219.1,221.5
XS GIS Cut Line= 4
     1593598.682      281645.275     1593511.777      282019.479
     1593488.261      282122.743     1593482.126      282351.763
#Sta/Elev= 30
    10.1   830.9      91  785.12   101.1  783.04   111.2  779.23   171.9  744.89
     182  740.92   192.1  739.09   262.8  734.81   333.6  734.93   343.7  736.51
   363.9  744.94   374.1  745.68   393.8   742.1   403.4  737.87     413  736.17
   422.7  732.15   432.3  725.15   440.2     721   451.6  719.09  458.67  720.96
   480.4  730.93     510  742.35     520  742.39   609.6  779.61   619.6  780.42
   629.5   783.8   669.4  800.54   689.3  812.03   699.3  816.44   719.2   818.1
#Mann= 3 , 0 , 0
    10.1      .1       0   440.2    .045       0  458.67      .1       0
Bank Sta=440.2,458.67
XS Rating Curve= 0 ,0
Exp/Cntr=0.3,0.1

Type RM Length L Ch R = 1 ,3052.1  ,27.2,26.5,25.9
XS GIS Cut Line= 4
     1593418.737      281631.984     1593311.383      281950.977
     1593269.464      282077.757     1593298.092      282259.746
#Sta/Elev= 30
     9.9  869.83    59.4   835.2    89.1  813.35      99  812.66   108.9  805.95
   138.6  780.75   178.2  742.95   188.1  736.07   207.9  732.68   257.4  727.83
   316.8  727.46   346.1  722.71   365.2  718.39   384.3  712.59   393.3  711.06
   403.3  710.77   413.3  711.08   422.4  712.13     432  714.71   441.5  718.76
     451  723.48   479.8  741.83   489.5  746.11   499.2  749.72   518.6  753.12
   567.1  769.56   605.8  788.43   615.5  790.16   625.2  793.34   654.3  806.17
#Mann= 3 , 0 , 0
       0      .1       0   393.3    .045       0   413.3      .1       0
Bank Sta=393.3,413.3
XS Rating Curve= 0 ,0
Exp/Cntr=0.3,0.1

Type RM Length L Ch R = 1 ,3025.6  ,93.6,93.7,93.7
XS GIS Cut Line= 4
     1593389.294      281620.626     1593295.744      281905.752
     1593242.834      282081.351     1593276.829      282267.814
#Sta/Elev= 30
      10  875.22      40  854.74      90   818.3     100  817.27     110  810.27
     150  777.02   190.1  739.89   200.1   734.4   210.1  733.74   220.1  731.22
   260.1  727.21     329  726.59   367.6  720.97   377.3  718.56  390.03  713.03
   396.6  710.76  404.98     713   435.2  723.43   464.2  726.63   473.8  729.22
   483.5   732.7   513.4  750.58   523.4  751.63   543.3  758.38   573.3  766.69
   593.2  774.65   613.2  784.89   633.1  789.96   653.1  799.51     673  806.09
#Mann= 3 , 0 , 0
      10     .06       0  390.03    .045       0  404.98     .06       0
Bank Sta=390.03,404.98
XS Rating Curve= 0 ,0
Exp/Cntr=0.3,0.1

Type RM Length L Ch R = 1 ,2931.9  ,42.2,43.3,44.5
XS GIS Cut Line= 4
     1593306.271      281608.468     1593192.272      281924.778
     1593154.698      282049.001      1593055.78      282245.432
#Sta/Elev= 30
     9.9  869.33      89  807.59   108.8  800.09   148.3  765.46   168.1  753.28
   187.9  737.36   197.8  731.08   207.7   729.2     267  723.91   306.6  724.84
   336.2  723.89   346.2  722.42   356.2  719.18   376.1  707.88   386.1   705.8
   396.1  707.15   416.1  717.58   426.1  717.41     466  735.37     496  743.83
     516     751     526  751.11     556  762.06     586  769.38     606  776.21
     616  780.12     626  787.15     636  789.35     646  793.98   685.9  819.98
#Mann= 3 , 0 , 0
       0     .06       0   376.1    .045       0   396.1     .06       0
Bank Sta=376.1,396.1
XS Rating Curve= 0 ,0
Exp/Cntr=0.3,0.1

Type RM Length L Ch R = 1 ,2888.6  ,217.6,219,220.5
XS GIS Cut Line= 4
     1593246.716      281608.213     1593151.631      281916.982
     1593120.959      282003.887     1593039.166       282233.93
#Sta/Elev= 30
    10.1  852.96    50.5  820.82    90.9  791.62     101  790.14   111.1  783.62
   171.6  736.31   181.7   730.2   191.8  727.67   252.4  722.61   292.8  723.63
   323.1  722.41   332.3  720.32   341.5  716.82   359.9  707.63  364.64  706.14
   369.2   704.7  381.35  706.27   396.8  711.92   415.2  714.46   434.8  720.46
   473.8  734.04   503.1  747.26   512.9  750.07   522.7  751.65     552  765.92
   571.5  771.48   581.3   775.7   600.8  785.96   620.3  791.36   659.4   815.2
#Mann= 3 , 0 , 0
    10.1      .1       0  364.64    .045       0  381.35      .1       0
Bank Sta=364.64,381.35
XS Rating Curve= 0 ,0
Exp/Cntr=0.3,0.1

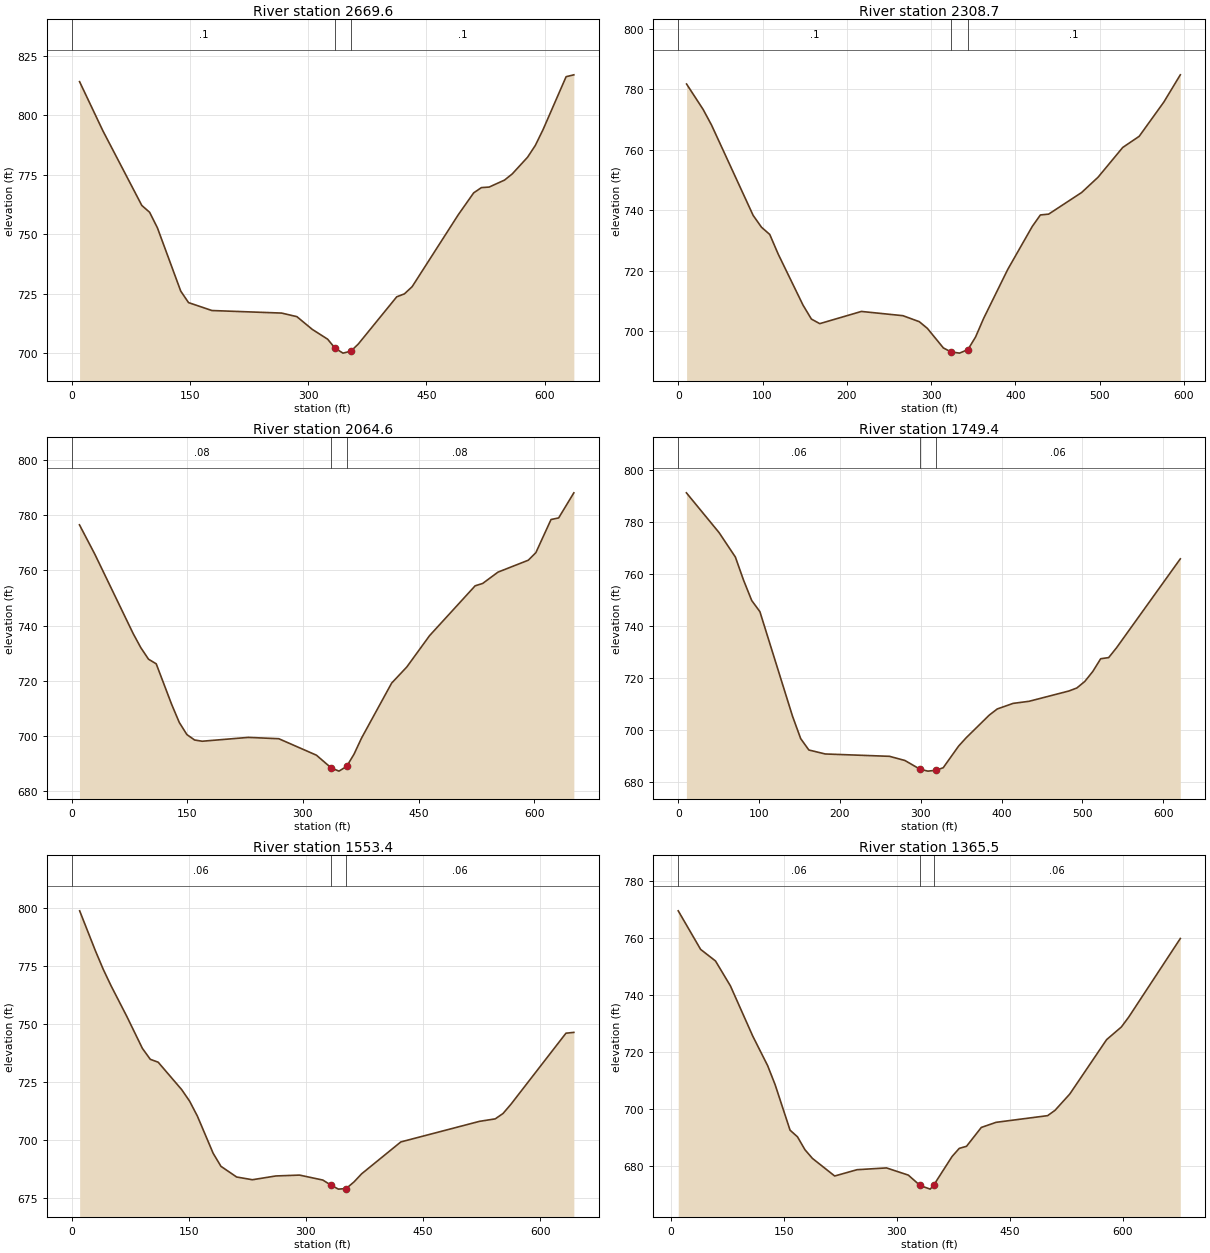
Type RM Length L Ch R = 1 ,2669.6  ,359,360.9,362.7
XS GIS Cut Line= 4
     1593078.017       281585.72     1592972.709      281787.135
      1592901.14      281957.879     1592834.683      282172.585
#Sta/Elev= 30
     9.9  814.22    39.5  793.55    88.9  762.17    98.8   759.3   108.7  752.76
   138.3  726.16   148.2  721.32   177.9  717.99   266.3  716.92   285.7  715.42
   305.2  710.07   324.7  705.95   334.2  702.15   344.2  700.08   354.2  700.89
   363.7  703.93   412.4  723.75   422.2     725     432  728.03   490.6   758.3
   510.1  767.47   519.9  769.67   529.7   769.9   549.2  772.83     559  775.42
   578.5  782.46   588.3   787.4   598.1  794.04   627.4  816.31   637.2  817.09
#Mann= 3 , 0 , 0
       0      .1       0   334.2    .045       0   354.2      .1       0
Bank Sta=334.2,354.2
XS Rating Curve= 0 ,0
Exp/Cntr=0.3,0.1

Type RM Length L Ch R = 1 ,2308.7  ,243.1,244.1,245.2
XS GIS Cut Line= 4
      1592774.36      281442.582     1592632.245      281679.782
     1592576.012      281790.203     1592536.138      281981.394
#Sta/Elev= 30
     9.9  781.69    29.6  773.27    39.5  768.14    88.9  738.28    98.8  734.38
   108.6  731.99   118.5  725.57   148.1  708.63     158  704.04   167.9  702.53
   217.3  706.56   266.6  705.16     286  703.18   295.6  700.97   314.6   694.5
   323.7  693.19   333.7  692.79   343.7  693.96   352.8  698.13   362.3  704.24
   390.9  720.41     420  734.62   429.7  738.44   439.5  738.71   478.6  745.85
   498.1   750.9   527.4  760.74   546.9  764.41   576.2  775.75   595.7  784.73
#Mann= 3 , 0 , 0
       0      .1       0   323.7    .045       0   343.7      .1       0
Bank Sta=323.7,343.7
XS Rating Curve= 0 ,0
Exp/Cntr=0.3,0.1

Type RM Length L Ch R = 1 ,2064.6  ,314,315.1,316.3
XS GIS Cut Line= 4
     1592510.578      281299.444     1592430.829      281545.846
     1592354.148      281681.827     1592287.691      281908.803
#Sta/Elev= 30
      10   776.5    29.9  765.88    79.7   737.1    89.6     732    99.6  727.82
   109.6  726.15   129.5  711.54   139.5  704.92   149.4  700.52   159.4  698.55
   169.3   698.1   229.1  699.49   268.7  699.01   317.5  693.05   336.8  688.42
   346.8  687.27   356.8     689   366.3   693.4   376.1  699.26   415.1  719.15
   434.8     725   464.4  736.37   523.5  754.41   533.3  755.27   553.1  759.36
   592.5  763.69   602.3  766.42     622  778.43   631.9  779.01   651.6   788.1
#Mann= 3 , 0 , 0
       0     .08       0   336.8    .045       0   356.8     .08       0
Bank Sta=336.8,356.8
XS Rating Curve= 0 ,0
Exp/Cntr=0.3,0.1

Type RM Length L Ch R = 1 ,1749.4  ,196.6,196.1,195.5
XS GIS Cut Line= 4
     1592266.221      281172.665     1592161.935      281391.461
     1592086.276      281512.106     1592027.998      281741.127
#Sta/Elev= 30
    10.1  791.38    50.5  776.07    70.7  766.63    80.8  757.74    90.9   749.9
     101  745.62   141.4  705.31   151.5  696.68   161.6  692.31   181.8  690.78
   261.4  689.87   280.4  688.27   298.8  684.96   308.8  684.17   318.8  684.49
   327.8  685.48   346.8   693.8   356.3  697.05   384.8  705.76   394.6  708.11
   414.3  710.27     434  711.07   483.3  715.04   493.1   716.2   502.9  718.71
   512.8  722.54   522.6  727.46   532.5  727.91   542.3  731.73   621.1  765.95
#Mann= 3 , 0 , 0
       0     .06       0   298.8    .045       0   318.8     .06       0
Bank Sta=298.8,318.8
XS Rating Curve= 0 ,0
Exp/Cntr=0.3,0.1

Type RM Length L Ch R = 1 ,1553.4  ,188,187.8,187.6
XS GIS Cut Line= 4
     1592100.256      281037.558     1591978.333      281313.609
     1591937.692      281381.855      1591873.28       281635.67
#Sta/Elev= 30
    10.1  798.68    30.2  781.52    40.2  773.55    50.3  766.38    70.4  753.23
    90.5  739.35   100.6  734.66   110.7  733.41   140.8  721.59   150.9  716.64
   160.9  710.18   181.1  694.14   191.1  688.52   211.2  683.91   231.4  682.74
   261.5  684.37   291.7  684.74   321.6   682.6   331.5  680.52   341.5  678.69
   351.5  678.95   361.4  681.76   371.3   685.3   421.5  699.04   522.2  707.91
   542.4  708.98   552.4   711.3   562.5  715.27     633  745.92   643.1  746.27
#Mann= 3 , 0 , 0
       0     .06       0   331.5    .045       0   351.5     .06       0
Bank Sta=331.5,351.5
XS Rating Curve= 0 ,0
Exp/Cntr=0.3,0.1

Type RM Length L Ch R = 1 ,1365.5  ,219,220.8,222.7
XS GIS Cut Line= 4
     1591955.407      280969.204     1591826.583      281203.337
     1591763.193      281311.713     1591692.647      281586.742
#Sta/Elev= 30
     9.9   769.4    39.6  755.92    59.4  751.85    79.2  743.14   108.9  725.56
   128.7   715.2   138.6  708.56   158.4  692.66   168.3  690.32   178.2  685.81
   188.1  682.79   217.7  676.62   247.4  678.83   286.5  679.45   315.5  676.93
  331.13   673.3   344.5  672.03  348.94  673.32   373.5  683.42   383.1  686.28
   392.8  687.02   412.4  693.61     432   695.4   500.5  697.74   510.3   699.6
   529.9   705.3   578.8  724.33   598.4  728.76   608.2  732.23   676.7  759.71
#Mann= 3 , 0 , 0
     9.9     .06       0  331.13    .045       0  348.94     .06       0
Bank Sta=331.13,348.94
XS Rating Curve= 0 ,0
Exp/Cntr=0.3,0.1

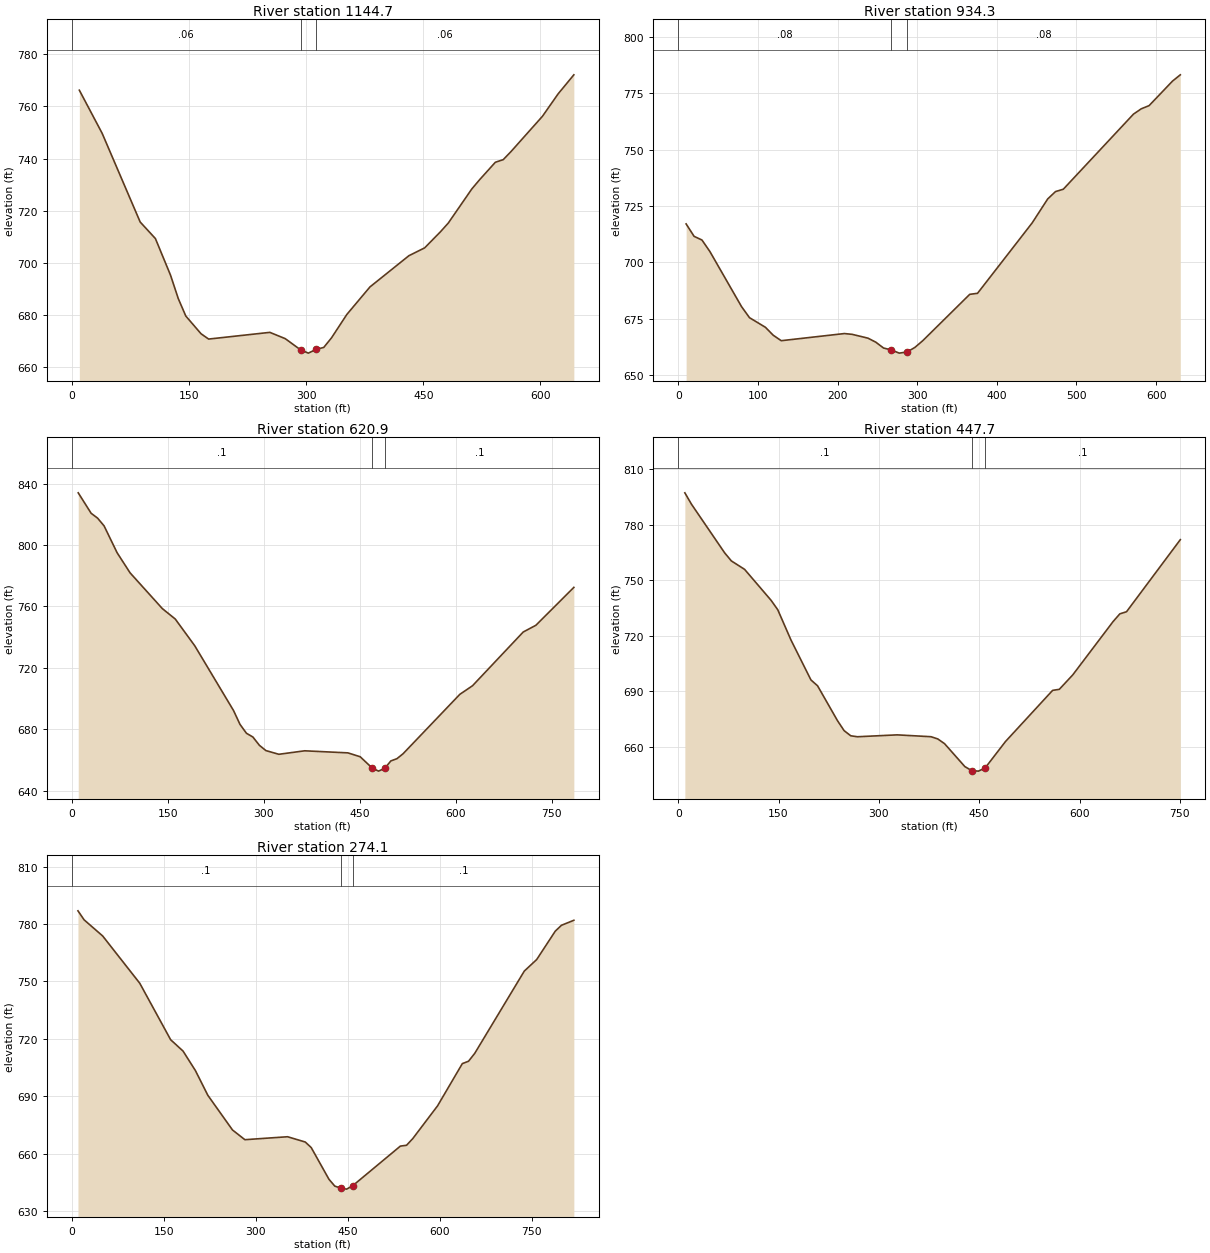
Type RM Length L Ch R = 1 ,1144.7  ,211.3,210.3,209.4
XS GIS Cut Line= 4
     1591748.879       280899.68     1591646.638      281087.804
     1591540.307      281242.189     1591415.572      281448.716
#Sta/Elev= 30
     9.7  766.23    38.9   749.7    87.6  715.69   107.1  709.34   126.5  695.27
   136.3  686.38     146  679.64   165.5  672.85   175.2  670.81   253.6  673.38
   273.3  670.97   292.9  666.69   302.9  665.42   312.9  666.87   322.6   667.6
   332.5  671.26   352.2  680.26   381.8  690.81   431.7  702.79   451.8  705.78
   471.9  711.91     482  715.27   512.2  728.38   522.2  731.93   542.3   738.6
   552.4  739.61   562.4  742.72   602.6  756.23   622.7  764.84   642.8  772.13
#Mann= 3 , 0 , 0
       0     .06       0   292.9    .045       0   312.9     .06       0
Bank Sta=292.9,312.9
XS Rating Curve= 0 ,0
Exp/Cntr=0.3,0.1

Type RM Length L Ch R = 1 ,934.3   ,312.8,313.5,314.2
XS GIS Cut Line= 4
     1591578.136      280847.537     1591450.334      280999.877
      1591355.25      281149.149     1591280.614      281392.484
#Sta/Elev= 30
     9.9  717.09    19.9  711.58    29.8  709.94    39.8   704.8    79.5  680.36
    89.5  675.45   109.4  671.21   119.3  667.66   129.3  665.24   208.7  668.41
   218.5  668.05   238.2  666.37     248   664.6   257.8  661.98   267.5  661.15
   277.5  659.72   287.5  660.25   297.2  662.27     307  665.23     366  685.82
   375.8  686.28   444.4  717.54   463.9  728.18   473.7  731.45   483.5   732.5
   571.6  765.84   581.4  768.21   591.2  769.61   620.6   780.5   630.4  783.29
#Mann= 3 , 0 , 0
       0     .08       0   267.5    .045       0   287.5     .08       0
Bank Sta=267.5,287.5
XS Rating Curve= 0 ,0
Exp/Cntr=0.3,0.1

Type RM Length L Ch R = 1 ,620.9   ,170.5,173.2,176
XS GIS Cut Line= 4
     1591436.021      280506.051     1591208.022      280802.551
      1591122.14       280929.33      1591025.01      281167.552
#Sta/Elev= 30
    10.1  834.01    30.3  820.67    40.4   817.5    50.5  812.47    70.8  795.02
      91  781.94   141.5  758.59   161.7  751.79   192.1   734.4   252.7  692.21
   262.8  683.18   272.9  677.38     283  674.92   293.2   669.5   303.3   666.1
   323.5  663.68   363.9  665.95   431.4   664.6   450.6  662.08   469.3  654.75
   479.3  652.71   489.3  654.64   498.4  659.32     508  660.82   517.6  664.03
   606.3  702.74   626.1  708.33   705.3  743.34   725.1  747.72   784.4  772.41
#Mann= 3 , 0 , 0
       0      .1       0   469.3    .045       0   489.3      .1       0
Bank Sta=469.3,489.3
XS Rating Curve= 0 ,0
Exp/Cntr=0.3,0.1

Type RM Length L Ch R = 1 ,447.7   ,175.6,173.6,171.6
XS GIS Cut Line= 4
      1591286.67      280446.986     1591082.187      280702.589
     1590957.452      280848.794     1590869.525      281062.479
#Sta/Elev= 30
     9.9  797.29    19.8  791.13    69.4  764.85    79.4  760.49    99.2  755.93
   138.9  739.15   148.8  734.09   168.6   717.7   198.4  696.15   208.3     693
   238.1  674.13     248  668.75   257.9  665.98   267.8  665.45   327.3  666.47
   377.9  665.47     388  664.27   398.1  661.73   428.5  649.32   438.7  647.16
   448.7  646.87   458.7  648.53   489.2  662.85   559.7  690.52   569.7  691.08
   589.8  698.88   650.1   727.7   660.2  731.87   670.2  733.02   750.6  771.97
#Mann= 3 , 0 , 0
       0      .1       0   438.7    .045       0   458.7      .1       0
Bank Sta=438.7,458.7
XS Rating Curve= 0 ,0
Exp/Cntr=0.3,0.1

Type RM Length L Ch R = 1 ,274.1   ,274.6,274.1,273.5
XS GIS Cut Line= 4
     1591190.641      280386.428     1590932.993      280597.046
      1590825.64      280745.296      1590762.25      281041.796
#Sta/Elev= 30
    10.1   786.9    20.2  782.17    50.4  773.76   110.9  749.06   161.3  719.52
   181.5   713.6   201.7   703.4   221.9  690.51   262.2  672.34   282.4  667.27
     352  668.81   380.9  666.05   390.6  663.15   419.5   646.6   429.1     643
   438.4  642.01   448.4  641.43   458.4  643.24     536  663.91   546.1  664.36
   556.2  667.82   596.7  684.96   637.1  707.03   647.2  708.28   657.3  712.38
   738.2  755.41   758.4  761.44   788.7  776.27   798.8  779.34     819  781.96
#Mann= 3 , 0 , 0
       0      .1       0   438.4    .045       0   458.4      .1       0
Bank Sta=438.4,458.4
XS Rating Curve= 0 ,0
Exp/Cntr=0.3,0.1

Chan Stop Cuts=-1
Use User Specified Reach Order=0